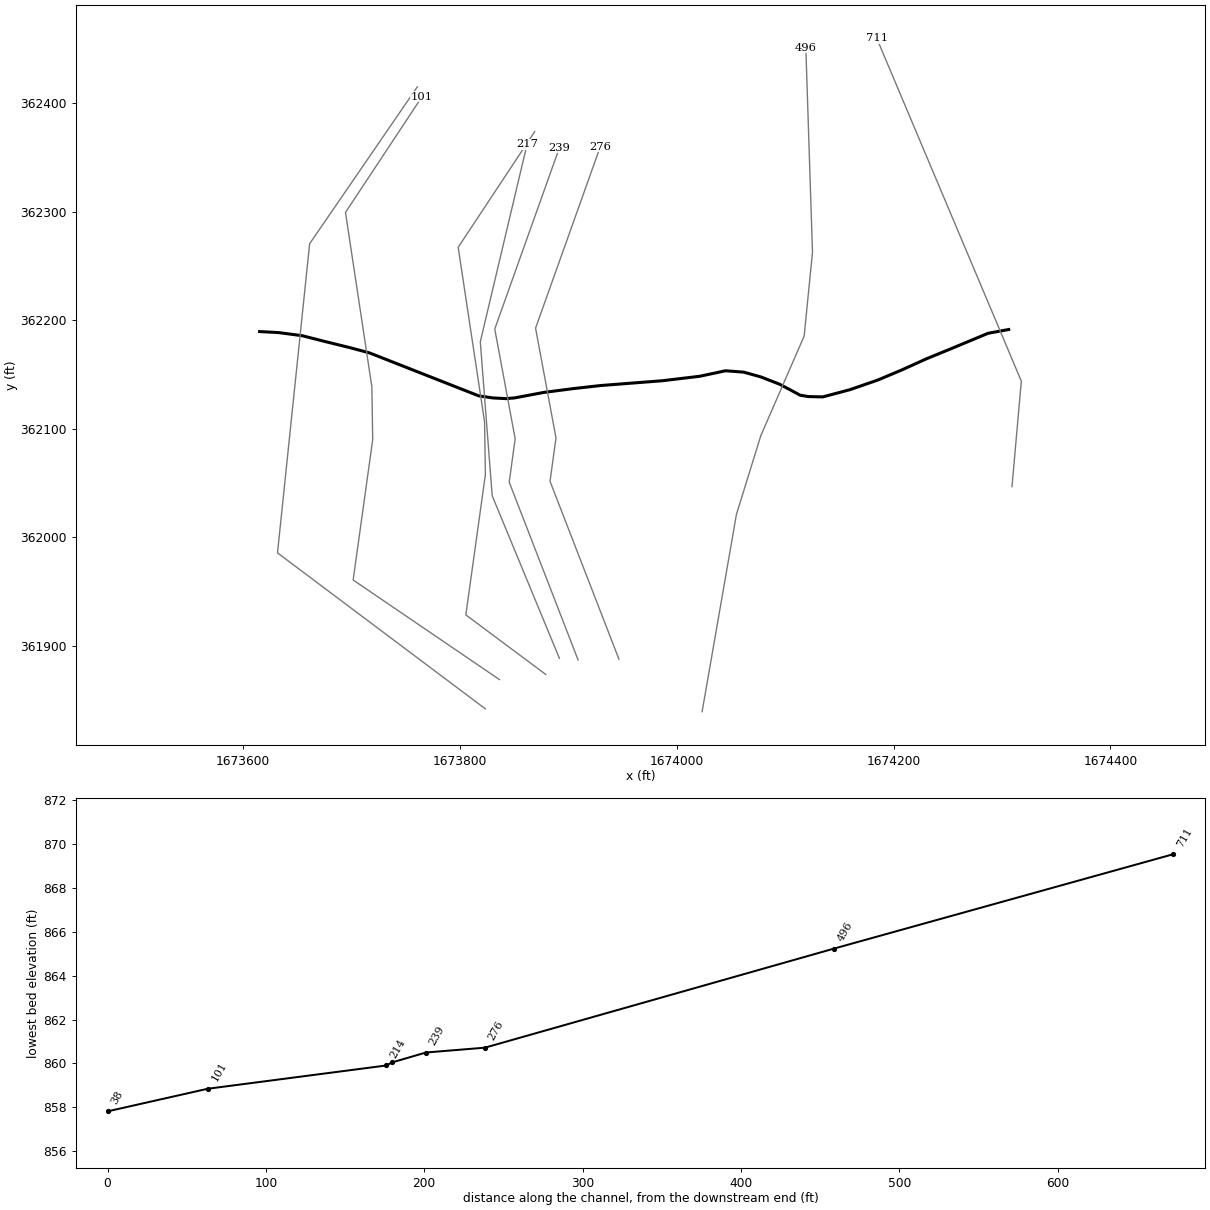
--- STOUTRN.prj (project) ---

Proj Title=STOUTRN
Current Plan=p01
Default Exp/Contr=0.3,0.1
English Units
Geom File=g01
Flow File=f01
Plan File=p01
Y Axis Title=Elevation
X Axis Title(PF)=Main Channel Distance
X Axis Title(XS)=Station
BEGIN DESCRIPTION:
---------- MODELED AS PART OF WVEMD CTP PROGRAM, 2023----------
Stream Name: Stout Run
Flood Zone:  AFH
Wetzel County, WV
HEC-RAS Version: RAS 6.3
Vertical Datum: NAVD88
Projection: NAD 1983 StatePlane West Virginia S FIPS 4702 (US Feet)
Terrain: 1-meter West Virginia FEMA R3 South Central (collected 2018-2020)
Land Use: 2019 NLCD
Hydrologic Method:
WV 2010 Regional Regression Equations
Additional Model Notes:
None
END DESCRIPTION:
DSS Export Rating Curves= 0
DSS Export Rating Curve Sorted= 0
DSS Export Volume Flow Curves= 0
DXF OffsetX= 0
DXF OffsetY= 0
DXF ScaleX= 1
DXF ScaleY= 10

--- STOUTRN.p01 (plan) ---

Plan Title=Floodplain
Program Version=6.30
Short Identifier=Floodplain
Geom File=g01
Flow File=f01
Subcritical Flow
K Sum by GR= 0
Std Step Tol= 0.01
Critical Tol= 0.01
Num of Std Step Trials= 20
Max Error Tol= 0.3
Flow Tol Ratio= 0.001
Split Flow NTrial= 30
Split Flow Tol= 0.02
Split Flow Ratio= 0.02
Log Output Level= 0
Friction Slope Method= 1
Unsteady Friction Slope Method= 2
Unsteady Bridges Friction Slope Method= 1
Parabolic Critical Depth
Global Vel Dist= 0 , 0 , 0
Global Log Level= 0
CheckData=True
Encroach Param=-1 ,0,0, 0
Computation Interval=1MIN
Output Interval=1HOUR
Instantaneous Interval=1HOUR
Mapping Interval=1HOUR
Computation Time Step Use Courant=        0
Computation Time Step Use Time Series=    0
Computation Time Step Count To Double=0
Computation Time Step Max Doubling=0
Computation Time Step Max Halving=0
Computation Time Step Residence Courant=0
Run HTab= 0
Run UNet= 0
Run Sediment= 0
Run PostProcess= 0
Run WQNet= 0
Run RASMapper=-1
UNET Theta= 1
UNET Theta Warmup= 1
UNET ZTol= 0.02
UNET ZSATol= 0.02
UNET MxIter= 20
UNET Max Iter WO Improvement= 0
UNET MaxInSteps= 0
UNET DtIC= 0
UNET DtMin= 0
UNET MaxCRTS= 20
UNET WFStab= 2
UNET SFStab= 1
UNET WFX= 1
UNET SFX= 1
UNET Gravity=32.17405
UNET 1D Methodology=Finite Difference
UNET DSS MLevel= 4
UNET Pardiso=0
UNET DZMax Abort= 100
UNET Use Existing IB Tables=-1
UNET Froude Reduction=False
UNET Froude Limit= 0.8
UNET Froude Power= 4
UNET D1 Cores= 0
UNET WindReference=Eulerian
UNET WindDragFormulation=Hsu (1988)
UNET D2 Coriolis=0
UNET D2 Cores= 0
UNET D2 Theta= 1
UNET D2 Theta Warmup= 1
UNET D2 Z Tol= 0.01
UNET D2 Volume Tol= 0.01
UNET D2 Max Iterations= 20
UNET D2 Equation= 0
UNET D2 RampUpFraction=0.1
UNET D2 TimeSlices= 1
UNET D2 Turbulence Formulation=None
UNET D2 Eddy Viscosity=0.3
UNET D2 Transverse Eddy Viscosity=0.1
UNET D2 Smagorinsky Mixing=0.05
UNET D2 BCVolumeCheck=0
UNET D2 Cores=0
UNET D2 SolverType=PARDISO (Direct)
UNET D2 Minimum Iterations= 3
UNET D2 Maximum Iterations= 30
UNET D2 Restart Number= 10
UNET D2 Relaxation Coeff=1.3
UNET D2 SOR Precondition Iterations= 10
UNET D2 ILUT Maximum Fill= 8
UNET D2 ILUT Tolerance=1E-08
UNET D2 Convergence Tolerance=0.00001
UNET D1D2 MaxIter= 0
UNET D1D2 ZTol=0.01
UNET D1D2 QTol=0.1
UNET D1D2 MinQTol=1
Write IC File= 0
Write IC File at Fixed DateTime=0
Write IC File at Sim End=0
Echo Input=False
Echo Parameters=False
Echo Output=False
Write Detailed= 0
HDF Write Warmup=0
HDF Write Time Slices=0
HDF Flush=0
HDF Compression= 1
HDF Chunk Size= 1
HDF Spatial Parts= 1
HDF Use Max Rows=0
HDF Fixed Rows= 1
Calibration Method= 0
Calibration Iterations= 20
Calibration Max Change=0.05
Calibration Tolerance=0.2
Calibration Maximum=1.5
Calibration Minimum=0.5
Calibration Optimization Method= 1
WQ AD Non Conservative
WQ ULTIMATE=-1
WQ Max Comp Step=1HOUR
WQ Output Interval=15MIN
WQ Output Selected Increments= 0
WQ Output face flow=0
WQ Output face velocity=0
WQ Output face area=0
WQ Output face dispersion=0
WQ Output cell volume=0
WQ Output cell surface area=0
WQ Output cell continuity=0
WQ Output cumulative cell continuity=0
WQ Output face conc=0
WQ Output face dconc_dx=0
WQ Output face courant=0
WQ Output face peclet=0
WQ Output face adv mass=0
WQ Output face disp mass=0
WQ Output cell mass=0
WQ Output cell source sink temp=0
WQ Output nsm pathways=0
WQ Output nsm derived pathways=0
WQ Create Restart=0
WQ Fixed Restart=0
WQ System Summary=0
WQ Write To DSS=0
Sorting and Armoring Iterations= 10
XS Update Threshold= 0.02
Bed Roughness Predictor= 0
Hydraulics Update Threshold= 0.02
Energy Slope Method= 1
Volume Change Method= 1
Sediment Retention Method= 0
Sediment TS Multiplier= 1
Warm Up Method= 0
XS Weighting Method= 0
Number of US Weighted Cross Sections= 1
Number of DS Weighted Cross Sections= 1
Upstream XS Weight=0
Main XS Weight=1
Downstream XS Weight=0
Number of DS XS's Weighted with US Boundary= 1
Upstream Boundary Weight= 1
Weight of XSs Associated with US Boundary= 0
Number of US XS's Weighted with DS Boundary= 1
Downstream Boundary Weight= 0.5
Weight of XSs Associated with DS Boundary= 0.5
Percentile Method= 0
Sediment Output Level= 3
Mass or Volume Output= 0
Output Increment Type= 1
Profile and TS Output Increment= 1
Transport Output Increment 1
XS Output Flag= 0
XS Output Increment= 10
Read HDF5 Sediment Hotstart= 0
Sediment Hotstart Type= 0
Write Gradation File= 0
Read Gradation Hotstart= 0
Write HDF5 File= 1
Write Binary Output= 1
Write DSS Sediment File= 0
DSS Sediment Output Type= 1
SV Curve= 0
Specific Gage Flag= 0
Subcell Erosion Methods= 0
Subcell Deposition Methods= 0
Advection Scheme= 1
Matrix Solver= 0
Implicit Weighting Factor= 1
Maximum Outer Loop Convergence Iterations= 5
Convergence Maximum Absolute= 0.001
Convergence RMSE= 0.0001
Grain Fractions Max Abs Error= 0.001
Max Subgrid Regions= 1
Max Subgrid Length Scale= 3.402823E+38
Initial Layer Thickness= 3.402823E+38
Min Layer Thickness= 3.402823E+38
Max Layer Thickness= 3.402823E+38
Number of Layers= 5

--- STOUTRN.f01 (steady flow) ---

Flow Title=Flow
Program Version=6.31
Number of Profiles= 1
Profile Names=F01pct
River Rch & RM=STOUTRN,Main,711
     568
Boundary for River Rch & Prof#=STOUTRN,Main            , 1
Up Type= 0
Dn Type= 3
Dn Slope=0.01623
DSS Import GetInterval= 0
DSS Import GetPeak= 0
DSS Import FillOption= 0

--- STOUTRN.g01 (geometry) ---

Geom Title=Geometry
Program Version=6.30

River Reach=STOUTRN         ,Main
Reach XY= 30
 1674306.1702843 362191.403540061674287.15162155362187.916670397
 1674251.3337798  362173.01906241674230.41354606362164.460680559
1674207.27448472362154.0007277281674185.40313739362144.808488891
1674159.72831997362135.9331785591674134.68735956362129.276695803
1674121.37472214362129.593624309 1674113.7671258362130.861338317
1674106.15985756362134.9820649771674094.74879114362141.004690722
1674077.63235556362147.6611734781674061.78363398362152.098828644
 1674044.9837988362153.3665426371674021.21088047362148.295030475
1673986.66075271362144.1743038151673929.60542063362139.736648649
1673904.24785981362136.8839640621673877.30500031362133.397422478
 1673850.3621408362128.3255822211673842.43794405362127.691725224
1673830.39302064362128.3255822211673817.39698364362130.227481306
1673716.59928498362169.8491212281673698.84899239  362174.6037049
1673675.70993106362180.3094021381673654.47244072362185.697842807
1673632.91834997362188.5505273941673615.27804997362189.504490914

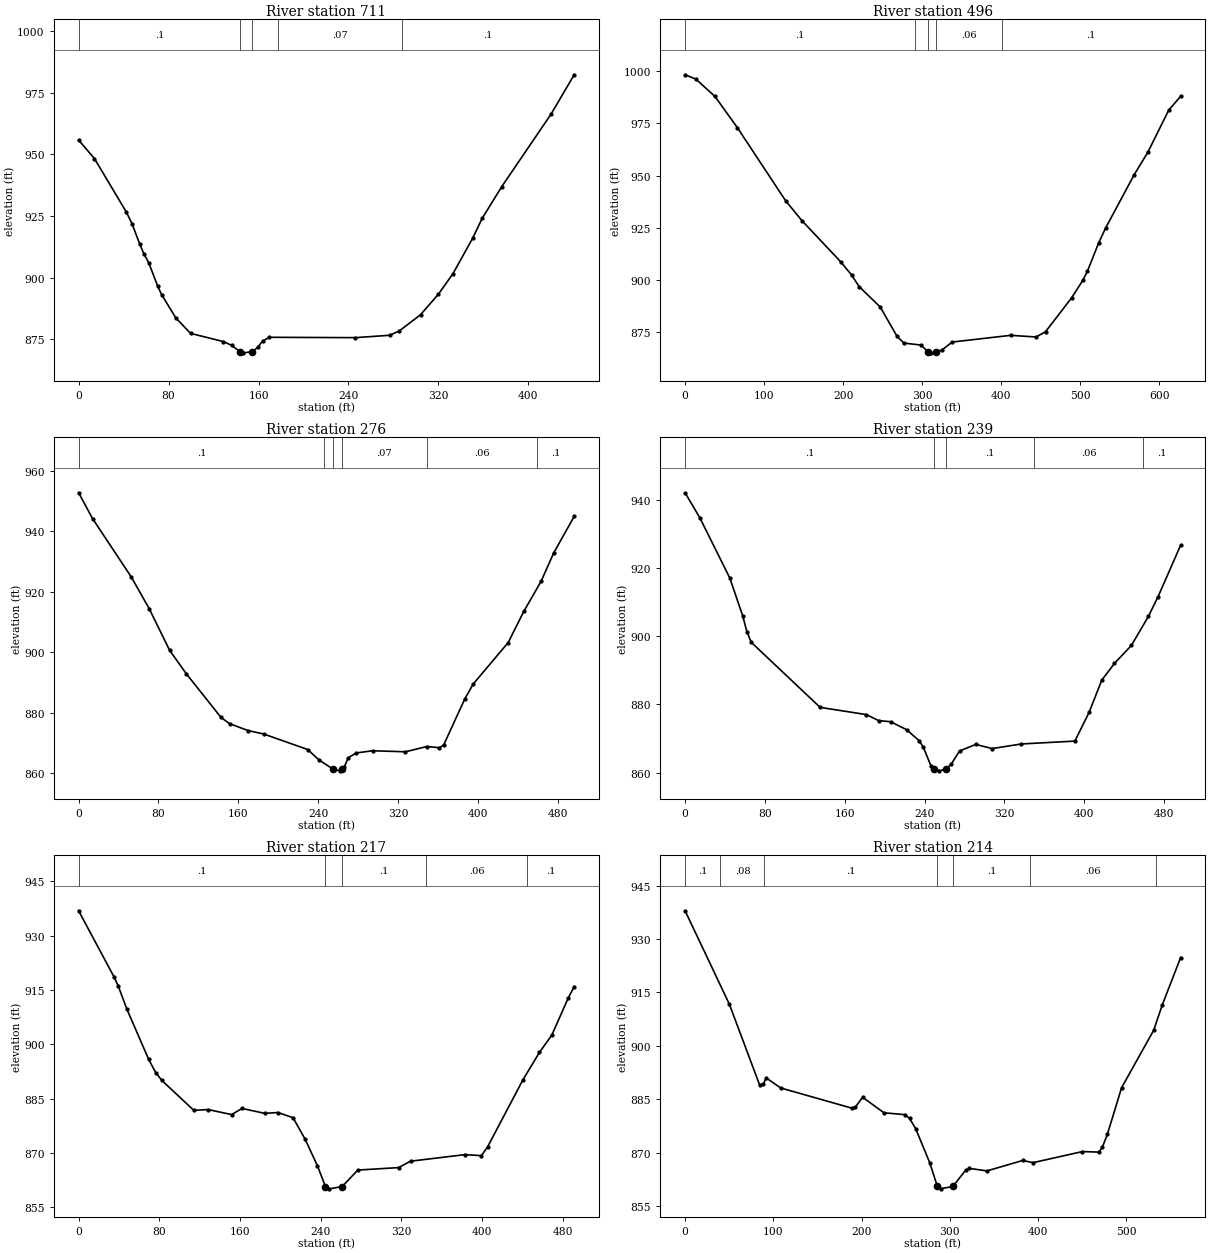
Type RM Length L Ch R = 1 ,711     ,217.1,214.4,208.8
XS GIS Cut Line= 3
1674309.17515811362046.5241160371674317.80331629362143.786990142
1674184.45905341362459.891330985
#Sta/Elev= 30
       0   955.8    14.1  948.29    42.2  926.79    47.5   921.9    54.2  913.78
    58.2  909.51    62.3  906.13    70.3   896.6    73.9  893.07    86.4  883.71
    99.5  877.43   128.8  874.09   136.1  872.57   143.6 869.985   146.2  869.53
   154.5  869.97   159.2  871.71   163.6  874.32   169.7  875.83   246.1  875.69
   276.5  876.65   285.1  878.39   304.1     885   319.9  893.28   332.9  901.62
   350.3   915.9   358.9  924.08   376.3  936.93   420.1   966.3   440.7  982.28
#Mann= 5 ,-1,0
       0      .1       0   143.6    .045       0   154.5      .1       0
  177.64     .07       0  287.64      .1       0
Bank Sta=143.6,154.5
XS Rating Curve= 0 ,0
Exp/Cntr(USF)=0,0
Exp/Cntr=0.3,0.1

Type RM Length L Ch R = 1 ,496     ,218.2,220.4,223.8
XS GIS Cut Line= 6
1674023.39493126361839.101423174  1674055.019868362020.890101582
1674077.53097785362093.5553105921674117.49841759362185.332029924
1674125.18180117362262.5907336771674119.03122292362451.360697344
#Sta/Elev= 30
       0  998.26    13.6   996.2    37.8   987.9    66.2  972.95   127.1  938.08
   147.9  928.48   196.8  908.86   210.8  902.44   220.3  896.92     247  887.17
   268.3  873.14     277   869.9   298.8  868.94   307.3 865.709   311.9  865.23
   317.2  865.71     325  866.55   338.1  870.39   412.2  873.61   444.3  872.81
   456.3  875.34   489.3  891.56   503.5  899.95   509.2   904.2   523.5  917.78
   532.3  924.93   568.4  950.38   585.9  961.29   612.3   981.4   627.3  987.96
#Mann= 5 ,-1,0
       0      .1       0  290.65     .06       0   307.3    .045       0
   317.2     .06       0  400.75      .1       0
Bank Sta=307.3,317.2
XS Rating Curve= 0 ,0
Exp/Cntr(USF)=0,0
Exp/Cntr=0.3,0.1

Type RM Length L Ch R = 1 ,276     ,37.2,37.2,37.4
XS GIS Cut Line= 5
1673946.65694275361887.5320907491673883.12232338362051.467096297
1673888.61296949362091.4703751631673869.78789709362192.655139354
1673929.40062638362359.727656971
#Sta/Elev= 30
       0   952.8    13.9  944.27    52.6     925    70.8  914.36    91.2  900.61
   107.9  892.86   142.6  878.43   151.2  876.34   169.7  874.07   185.3  872.93
   229.5  867.78   240.8  864.34   255.3  861.19     262  860.72   263.5  861.17
   266.1  861.98   270.2  865.07   278.3  866.65   294.6  867.37   327.5  867.03
     349  868.78   361.5  868.38   365.7  869.25   386.9  884.54   395.4  889.49
   430.4  903.21     446  913.49   463.4  923.51   476.1  932.94   496.5  944.96
#Mann= 6 ,-1,0
       0      .1       0  246.19     .07       0   255.3    .045       0
   263.5     .07       0  349.12     .06       0  459.12      .1       0
Bank Sta=255.3,263.5
XS Rating Curve= 0 ,0
Exp/Cntr(USF)=0,0
Exp/Cntr=0.3,0.1

Type RM Length L Ch R = 1 ,239     ,21.7,21.4,20.6
XS GIS Cut Line= 5
1673909.00679794361886.7477127321673845.47217856 362050.68271828
1673850.96282468362090.6859971461673832.13775227362191.870761337
1673891.75048156362358.943278953
#Sta/Elev= 30
       0  942.18    14.8  934.82    44.8  917.14    57.7  906.04      62  901.29
    66.3  898.25   135.3  879.14   181.7  877.02   193.8  875.27     206  874.92
   222.1  872.56   234.4  869.36   238.4  867.63   246.6  861.78   249.3861.0018
   254.7   860.5   261.8861.0242   266.9  862.59     275  866.35   291.3  868.26
   307.6  867.04   336.8  868.39   390.5  869.24   404.8  877.68   417.5  887.15
   430.2  892.06   447.2  897.35   464.2  905.88   473.8   911.6   496.5  926.79
#Mann= 5 ,-1,0
       0      .1       0   249.3    .045       0   261.8      .1       0
  349.12     .06       0  459.12      .1       0
Bank Sta=249.3,261.8
XS Rating Curve= 0 ,0
Exp/Cntr(USF)=0,0
Exp/Cntr=0.3,0.1

Type RM Length L Ch R = 1 ,217     ,2.9,3.6,4.4
XS GIS Cut Line= 4
1673891.75048156361888.3164687651673829.78461822362038.132670009
1673818.80332598362180.1050910821673861.94411692362362.080791021
#Sta/Elev= 30
       0   936.9    34.9  918.73    39.2  916.17    47.9  909.69    69.5  895.81
    76.4   892.2    82.5  890.02   114.2  881.75   128.5  881.96   151.7  880.57
   162.1  882.27   184.6  880.91   197.7  881.14   212.7   879.7   224.7  873.74
   236.8  866.46   244.8  860.68   248.8  860.05   261.4860.6895   276.9  865.24
   317.3  865.92   329.2  867.69   383.1   869.5   399.5  869.23   405.7  871.69
   440.6  890.14   457.1  897.78   469.4  902.58   485.8  912.91   491.5  915.92
#Mann= 5 ,-1,0
       0      .1       0   244.8    .045       0   261.4      .1       0
  344.52     .06       0  444.52      .1       0
Bank Sta=244.8,261.4
XS Rating Curve= 0 ,0
Exp/Cntr(USF)=0,0
Exp/Cntr=0.3,0.1

Type RM Length L Ch R = 1 ,214     ,115.2,112.8,112.2
XS GIS Cut Line= 6
1673879.20043329361873.4132864431673805.46889969361928.319747632
1673823.50959409362057.7421204331673822.72521607362106.373557486
1673798.40949754362267.1710509671673869.00351907362373.846461276
#Sta/Elev= 30
       0  937.91    50.2  911.69    84.5  889.04    88.6  889.34    92.1  891.01
   108.3  888.21   189.1  882.54   193.1  882.85   201.2  885.61   225.4  881.25
   249.4  880.71   254.5  879.67   261.4  876.78   277.5  867.14     286  860.59
   289.6  859.91   303.6860.5913   317.9  865.09     322  865.66   342.2  864.94
   382.7  867.86   394.6  867.26   450.5  870.37   469.1  870.21   473.2  871.68
   478.7  875.18   494.9   888.3   531.2  904.37     541  911.52   561.8   924.8
#Mann= 7 ,-1,0
       0      .1       0      40     .08       0      90      .1       0
     286    .045       0   303.6      .1       0  391.24     .06       0
  533.87      .1       0
Bank Sta=286,303.6
XS Rating Curve= 0 ,0
Exp/Cntr(USF)=0,0
Exp/Cntr=0.3,0.1

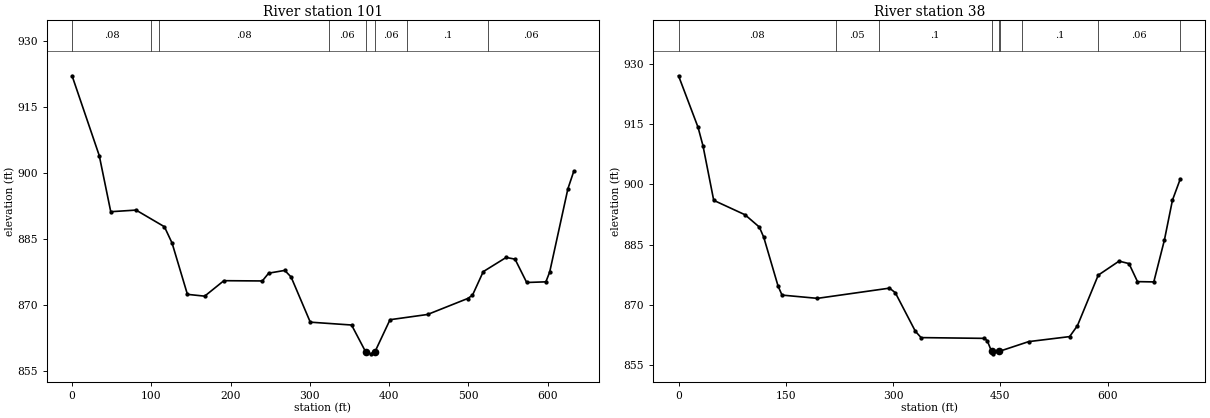
Type RM Length L Ch R = 1 ,101     ,64.5,63.3,61.4
XS GIS Cut Line= 6
1673836.45183137361868.7070183411673701.53881244361960.479246328
1673719.57950683362089.9016191291673718.79512882362138.533056182
1673694.47941029362299.3305496631673765.07343182362406.005959972
#Sta/Elev= 30
       0  922.14    34.3  903.97    48.8   891.2    80.7  891.57   116.5  887.78
   126.2  884.04   145.5  872.39   167.3  871.98   191.5   875.5     240  875.44
     248  877.21   268.3  877.84   276.3  876.34   300.5  866.06   352.6  865.41
   370.3  859.32   376.9  858.85   382.1859.3252   401.1  866.62   448.5  867.81
     499  871.44   505.1  872.19   518.7  877.56   547.6  880.79   558.8   880.4
   573.5  875.09   597.7  875.24   602.5  877.46   625.5  896.43     633  900.46
#Mann= 8 ,-1,0
       0     .08       0     100      .1       0     110     .08       0
  323.84     .06       0   370.3    .045       0   382.1     .06       0
  422.48      .1       0   525.1     .06       0
Bank Sta=370.3,382.1
XS Rating Curve= 0 ,0
Exp/Cntr(USF)=0,0
Exp/Cntr=0.3,0.1

Type RM Length L Ch R = 1 ,38      ,,,
XS GIS Cut Line= 4
1673823.50959409361841.6895533121673631.77274549361985.492189758
1673661.40480391362270.4828692611673760.75935273362415.157036837
#Sta/Elev= 30
       0  927.02    27.3  914.19    34.2  909.59    49.2  896.02      93  892.43
     113  889.37   119.2  886.81   139.2  874.68   144.7  872.44   194.2  871.63
     295  874.17   303.1  873.04   331.2  863.43   339.2  861.86   427.7  861.67
   431.7  861.09   437.7858.4495   439.8  857.82   448.1858.4137   489.6  860.86
   546.9  862.11   557.8  864.82   586.9   877.4     616  880.89   629.9  880.28
   641.8  875.79   664.6  875.72   679.4  886.11   690.7  896.07   701.7  901.37
#Mann= 9 ,-1,0
       0     .08       0     220     .05       0  279.67      .1       0
   437.7    .045       0   448.1      .1       0  449.67     .06       0
  479.67      .1       0   586.2     .06       0   701.7      .1       0
Bank Sta=437.7,448.1
XS Rating Curve= 0 ,0
Exp/Cntr(USF)=0,0
Exp/Cntr=0.3,0.1
LCMann Table=0

Chan Stop Cuts=-1
Use User Specified Reach Order=0
Composite Channel Slope=5